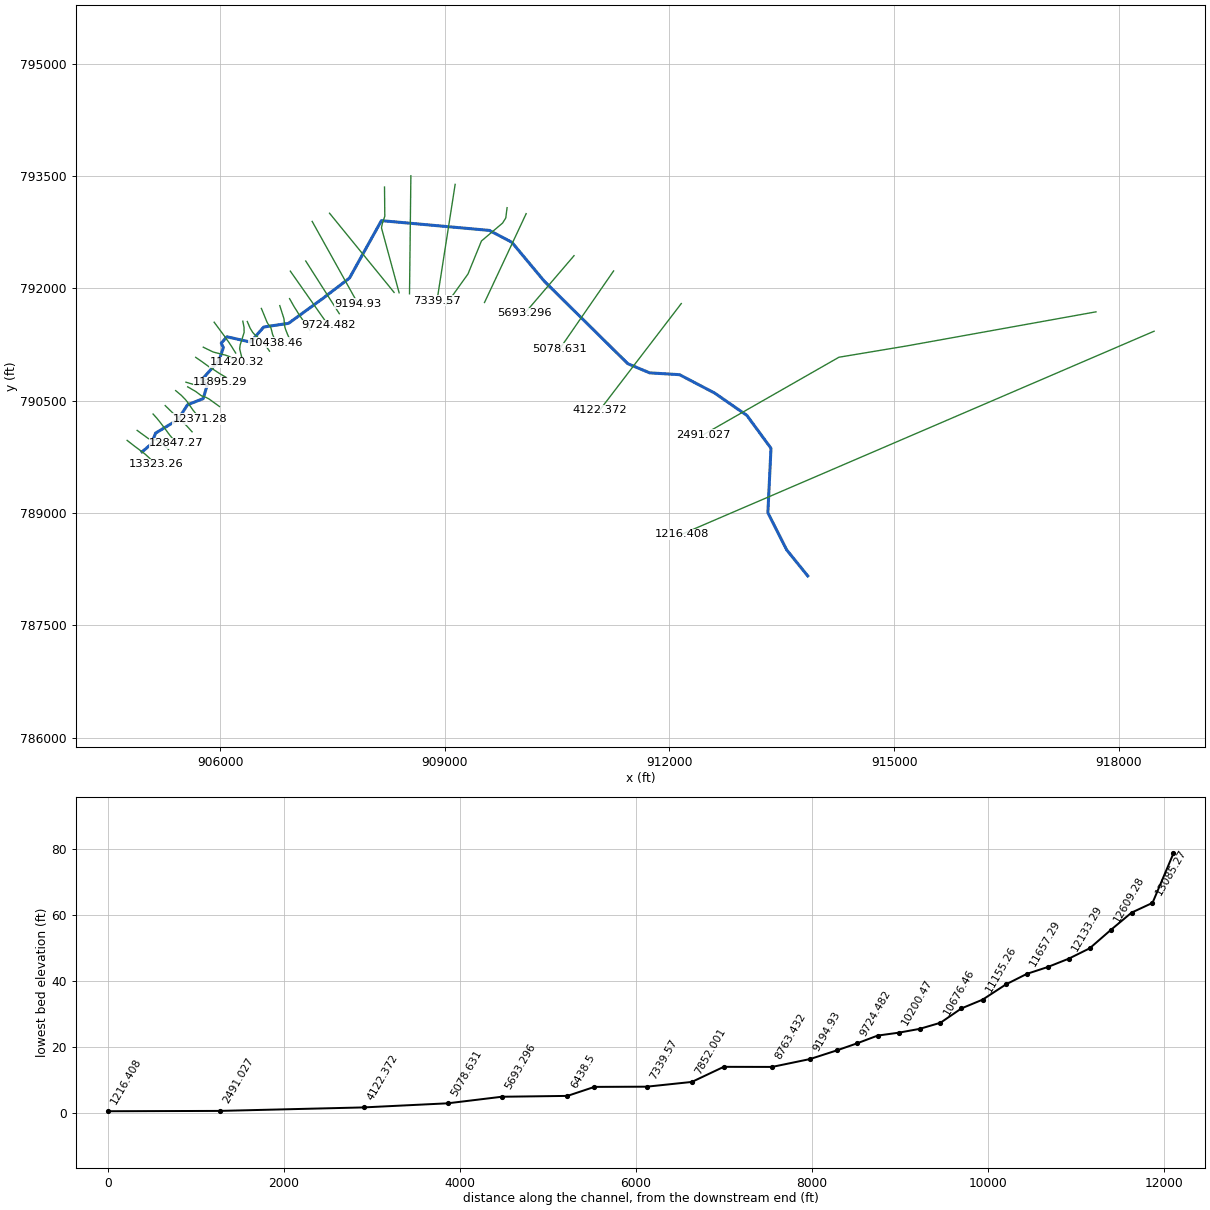
--- 12026_ras.prj (project) ---

Proj Title=12026
Current Plan=p01
Default Exp/Contr=0.3,0.1
English Units
Geom File=g01
Flow File=f01
Plan File=p01
Y Axis Title=Elevation
X Axis Title(PF)=Main Channel Distance
X Axis Title(XS)=Station
BEGIN DESCRIPTION:
RFD model 12026 exported to HEC-RAS
END DESCRIPTION:

--- 12026_ras.p01 (plan) ---

Plan Title=Plan 01
Program Version=4.10
Short Identifier=Plan 01
Geom File=g01
Flow File=f01
Subcritical Flow
Calc Critical at every XS
Secant Critical Depth

--- 12026_ras.f01 (steady flow) ---

Flow Title=Flow 01
Program Version=5.01
Number of Profiles= 6
Profile Names=10yr,25yr,50yr,100yr,100plus,500yr
River Rch & RM=12026,29,13323.26
  178.18  286.48  387.97  481.22  702.59 1218.13
River Rch & RM=12026,29,11895.29
  179.76  289.02  391.42  485.51  708.84 1227.47
River Rch & RM=12026,29,11657.29
  188.73  303.51  411.13     510   744.6 1280.65
River Rch & RM=12026,29,11420.32
  191.84  308.53  417.95  518.47  756.97 1298.94
River Rch & RM=12026,29,11155.26
  215.91  347.42  470.84  584.21  852.95 1439.67
River Rch & RM=12026,29,10914.45
  218.96  352.34  477.51  592.49  865.04 1457.15
River Rch & RM=12026,29,10676.46
  331.25  533.29  723.23  897.35 1310.14 2080.07
River Rch & RM=12026,29,10438.46
  332.65  535.53  726.29  901.15 1315.68 2087.65
River Rch & RM=12026,29,10200.47
   338.2  544.51   738.5  916.32 1337.83 2117.84
River Rch & RM=12026,29,9962.476
  401.14  646.09  876.61 1087.79 1588.17 2453.96
River Rch & RM=12026,29,9724.482
   439.9  708.89  962.24 1194.33 1743.73  2660.2
River Rch & RM=12026,29,9501.546
  448.06  722.09  980.23 1216.71 1776.39 2703.08
River Rch & RM=12026,29, 9194.93
   463.3  746.77 1013.86 1258.54 1837.46 2782.99
River Rch & RM=12026,29,8763.432
  468.76  755.63 1025.94 1273.57 1859.41 2811.67
River Rch & RM=12026,29,8214.349
  690.46 1115.61 1517.56 1885.93 2753.46 3947.02
River Rch & RM=12026,29,7852.001
  695.77 1124.23 1529.33 1900.61 2774.89 3973.51
River Rch & RM=12026,29, 7339.57
  824.12 1332.12 1812.82  2253.1 3289.53 4598.58
River Rch & RM=12026,29,6745.541
     841 1359.61 1850.47 2300.09 3358.13 4681.56
River Rch & RM=12026,29,  6438.5
  884.25 1429.99 1946.74 2420.12 3533.37 4891.96
River Rch & RM=12026,29,5693.296
  985.54 1594.52 2171.58 2700.13  3942.2 5375.81
River Rch & RM=12026,29,5078.631
  1007.5 1630.43 2220.88 2761.78  4032.2 5482.43
River Rch & RM=12026,29,4122.372
 1100.49 1782.16 2428.84 3021.44  4411.3 5926.25
River Rch & RM=12026,29,2491.027
 1178.58 1910.27 2605.08 3242.19  4733.6 6302.28
River Rch & RM=12026,29,1216.408
 1190.81 1930.47 2632.98 3277.27 4784.81 6362.25
Boundary for River Rch & Prof#=12026,29,1
Up Type= 0
Dn Type= 2
Boundary for River Rch & Prof#=12026,29,2
Up Type= 0
Dn Type= 2
Boundary for River Rch & Prof#=12026,29,2
Up Type= 0
Dn Type= 2
Boundary for River Rch & Prof#=12026,29,2
Up Type= 0
Dn Type= 2
Boundary for River Rch & Prof#=12026,29,2
Up Type= 0
Dn Type= 2
Boundary for River Rch & Prof#=12026,29,2
Up Type= 0
Dn Type= 2

--- 12026_ras.g01 (geometry) ---

Geom Title=12026
Program Version=4.10

River Reach=12026,29
Reach XY= 30
904958.815873682789817.374775827905084.517461449 789922.61832118
905139.204961479790067.583598986905435.993569165790245.851171479
905566.337060302790445.451409578905774.356459796790527.712547421
905826.704961449790699.528043404905755.524405867790779.389154524
905987.929229289791039.163436159906044.179988712791209.356128111
906015.871319741791268.876919121906092.086966783791353.802925825
 906407.21711421791282.861376777906583.476377279791483.829811946
 906914.13120541791532.758269608907371.925988227791865.007191285
907728.831697583792137.896099001908154.178919762792903.955126747
909594.934128106792773.746793419909895.281350344  792615.7606823
910329.309128106792094.927348956911444.254151762790993.907383502
911735.269776285790871.837071195912134.575331807790847.531515628
912603.614683658790601.871793419 913034.17023924  790303.2606823
913355.504729956789864.969594359  913313.8380633789004.292511061
913565.140146613788508.198761061913846.390146613788160.542511046

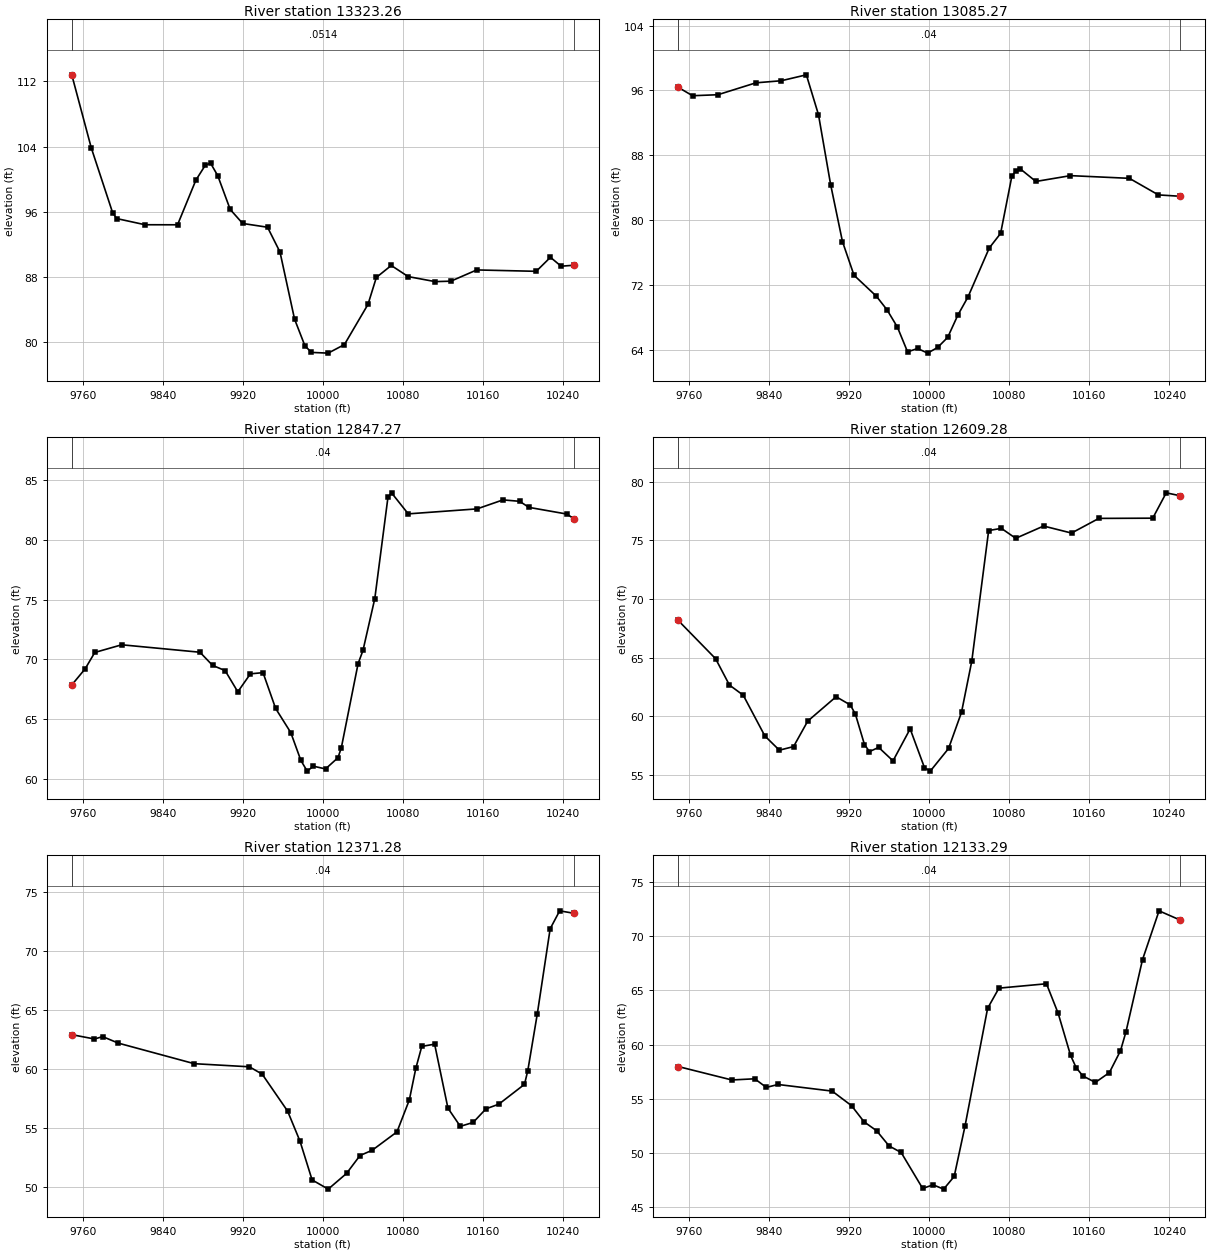
Type RM Length L Ch R = 1 ,13323.26,237.994100,237.994100,237.994100
XS GIS Cut Line= 6
904759.669037097789970.142362637904857.431185965789893.714990522
904967.291418223789812.327331248 904998.80230838789787.344475444
905056.690785781789734.914674452905144.049785285789648.551115697
#Sta/Elev= 30
9749.005112.81759768.465103.84939789.82895.866359793.85295.137159822.30194.37629
9854.774 94.37029873.09799.864289882.516 101.6979887.738101.95669894.961100.4079
9907.405 96.2579 9919.8594.53419 9944.7494.069489957.18491.018529971.738 82.7684
9982.07479.496349988.53878.6724810005.3478.5831410021.6179.6368110045.1884.58525
10053.5387.8946510068.4289.3668810085.3887.9966510112.36  87.37910128.0187.43359
10153.8888.8166510213.36 88.647210227.5890.3719410238.25 89.275510250.9889.39401
#Mann= 3 , 0 , 0
9749.005  0.0514       09749.005  0.0514       010250.98  0.0514       0
#XS Ineff= 2 , 0
       0                               0
Bank Sta=9749.005,10250.98
Exp/Cntr=0.3,0.1

Type RM Length L Ch R = 1 ,13085.27,237.994100,237.994100,237.994100
XS GIS Cut Line= 6
 904893.72153311790103.294279025905043.285084613789994.343500003
905080.591822923789981.736199838905143.742157011789977.495771903
905188.746611489789957.375678359905312.236076035789849.861645786
#Sta/Elev= 30
9749.08996.379759763.37495.343419788.70695.466429826.70496.936429852.03697.19127
9877.12897.922519889.25193.003479901.37484.388999913.216 77.34549924.773 73.1899
9947.09370.607619957.78768.919029968.09366.79926 9978.2863.738399988.31764.15556
 9998.3363.5819410008.3564.2859510018.3965.5290510028.5268.2684310038.7170.52146
10059.9476.5588710071.2678.3545110082.5785.4518210086.8186.0792510091.0286.30732
10106.5184.7641310141.1185.4834910199.9985.1502710228.9583.1057810250.8682.93577
#Mann= 3 , 0 , 0
9749.089    0.04       09749.089    0.04       010250.86    0.04       0
#XS Ineff= 2 , 0
       0                               0
Bank Sta=9749.089,10250.86
Exp/Cntr=0.3,0.1

Type RM Length L Ch R = 1 ,12847.27,237.994200,237.994200,237.994200
XS GIS Cut Line= 6
905106.068983911790322.079050884 905148.62909293790274.926755587
905183.545278008 790232.95619278 905256.04202135790138.637882498
 905326.30956778790043.599274574905419.380161747789930.249032769
#Sta/Elev= 30
9749.01767.850299762.34669.195289772.02470.572279798.96771.215679877.167 70.5911
9889.77969.490379902.33769.052489915.00567.276419927.61868.78195 9940.2368.88022
9952.84365.877839967.97463.858119978.06861.523729984.38360.629059990.55261.04418
10002.7160.8126510015.1961.7566410018.5562.6053110035.2669.6325710040.1570.74241
10051.9875.0926710065.1183.5679710068.69 83.9488 10085.482.1859510154.2582.60425
10180.1383.3571310196.7983.23771   1020682.7306210244.07 82.168810250.9781.77457
#Mann= 3 , 0 , 0
9749.017    0.04       09749.017    0.04       010250.97    0.04       0
#XS Ineff= 2 , 0
       0                               0
Bank Sta=9749.017,10250.97
Exp/Cntr=0.3,0.1

Type RM Length L Ch R = 1 ,12609.28,237.994100,237.994100,237.994100
XS GIS Cut Line= 6
905267.984194173790434.812975517905420.569227226790285.994761348
905472.321444672 790244.41377266905509.357591061790210.420248912
 905560.86050024790157.461046896905626.704194554790084.546976616
#Sta/Elev= 30
9749.03668.163539786.39164.903269800.21862.660579814.04661.792069835.64458.31947
9850.124 57.10869864.31157.413579878.49559.586479906.86361.665239921.04760.96405
9926.13460.182239935.23157.588139940.23456.988719949.41557.347019963.75356.19817
9980.87858.924879995.22555.61461   1000155.3236110019.2857.2529210032.2260.33533
 10042.564.6983410059.3775.8280110072.0876.0149210086.42 75.166510114.3176.21231
10142.21  75.61410169.5276.8638810223.4176.8824410236.89 79.042910250.9778.78947
#Mann= 3 , 0 , 0
9749.036    0.04       09749.036    0.04       010250.97    0.04       0
#XS Ineff= 2 , 0
       0                               0
Bank Sta=9749.036,10250.97
Exp/Cntr=0.3,0.1

Type RM Length L Ch R = 1 ,12371.28,237.994100,237.994100,237.994100
XS GIS Cut Line= 6
905407.552368693790634.785677205905481.340029837790573.252912573
905538.678080087790514.558534794905565.931721314790479.886962601
905637.058220508790376.942988308 905733.87730936790256.546535637
#Sta/Elev= 30
9749.05262.91271 9771.77 62.54479779.94562.745969795.55962.194319871.50560.44908
 9926.6260.185179939.37959.562929964.81856.426469977.22453.871019989.30350.58598
10005.4249.8041810023.73 51.1351 10037.252.6557110049.41  53.10410074.1554.66145
10086.5157.3732110092.98 60.048310098.9761.91695 10111.862.1052810125.1156.67662
10137.4755.13334 10150.355.4618510163.1356.6176710175.9757.0124810201.6358.69644
 10204.959.8398310214.4664.68335 10227.3 71.897810236.8173.4208710250.9873.21244
#Mann= 3 , 0 , 0
9749.052    0.04       09749.052    0.04       010250.98    0.04       0
#XS Ineff= 2 , 0
       0                               0
Bank Sta=9749.052,10250.98
Exp/Cntr=0.3,0.1

Type RM Length L Ch R = 1 ,12133.29,237.994200,237.994200,237.994200
XS GIS Cut Line= 6
905568.287496024790684.945246201905675.009814956790623.346864929
905751.998101653790565.608280077905811.992640448790544.577771366
905854.796198151 790521.84242395905992.647997483790422.163832114
#Sta/Elev= 30
9749.09857.976349802.64956.736539825.576 56.84549837.10156.050469848.84456.31965
9902.92355.70937 9922.3354.36224 9934.8352.87227 9947.3352.05335 9959.8350.64663
9971.89250.042449993.39146.7242510003.8547.0571410014.3746.66059 10024.947.83097
10035.6652.45514 10058.363.3480310069.6365.2129110117.1265.6177810128.8262.89017
10141.2259.0058310146.7457.8858910153.4557.11254   1016656.5100210180.01 57.4179
 10191.159.4325910196.5661.1710510213.1167.8409610229.6672.34971 10250.971.49087
#Mann= 3 , 0 , 0
9749.098    0.04       09749.098    0.04       0 10250.9    0.04       0
#XS Ineff= 2 , 0
       0                               0
Bank Sta=9749.098,10250.9
Exp/Cntr=0.3,0.1

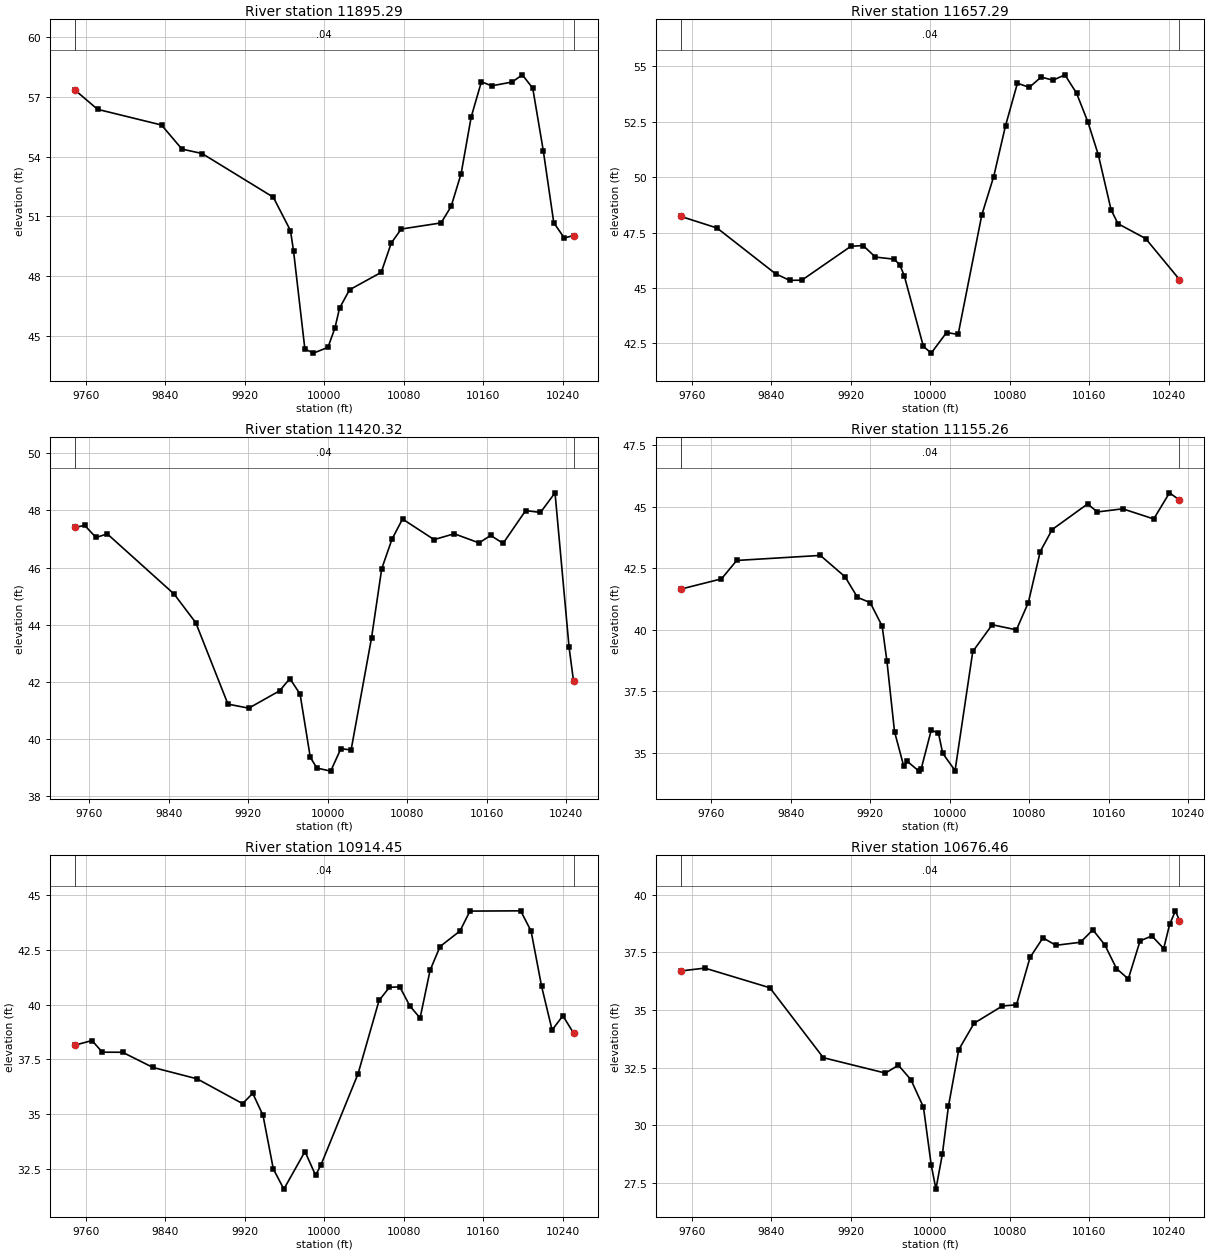
Type RM Length L Ch R = 1 ,11895.29,238.006800,238.006800,238.006800
XS GIS Cut Line= 6
905544.308727822790747.298259268905683.699477912790705.588787921
905741.020413246790718.803665018905781.753117321 790769.93410542
905817.568738505790782.027719909906003.782853652790748.770856056
#Sta/Elev= 30
9749.31457.348499772.06156.379769836.35455.592099856.90554.382599877.13154.16079
9948.78351.96526 9966.0350.289039969.118 49.26749980.51444.344269989.15144.13556
10003.7544.4263710010.7345.3942710015.41 46.396210025.4447.3165610057.3248.19279
10067.3749.6616410077.3850.3667710117.51 50.675910127.5951.5021510137.6653.14896
10147.7455.9875510158.03 57.764510168.3357.5607710188.9257.7499110199.2258.11282
10209.6857.4406510220.2654.3112210230.8350.6850910241.4149.9176810250.6950.04085
#Mann= 3 , 0 , 0
9749.314    0.04       09749.314    0.04       010250.69    0.04       0
#XS Ineff= 2 , 0
       0                               0
Bank Sta=9749.314,10250.69
Exp/Cntr=0.3,0.1

Type RM Length L Ch R = 1 ,11657.29,236.970100,236.970100,236.970100
XS GIS Cut Line= 6
905675.003882784791078.918955176905750.219042478791027.362348309
905858.546734447790949.113966752905905.485177419790920.767681034
905999.352495415790859.459101737906094.358631553790803.635455222
#Sta/Elev= 30
9748.86648.228289785.23347.705169844.089 45.64059858.28945.341989870.62545.34982
9919.968 46.88039932.30446.91367 9944.6446.393519963.63546.297419969.31246.03493
9973.68845.552879992.973 42.359110000.8642.05504 10016.342.9861610027.9642.89838
10051.8348.3010910063.7850.0306910075.7252.3329610087.6654.2451110099.6154.05591
10111.5554.52321 10123.554.3798310135.4454.6234710147.1953.7957410158.79 52.4717
10169.1850.9967910181.9848.5235610188.9247.9000610216.7847.2281710250.8345.37733
#Mann= 3 , 0 , 0
9748.866    0.04       09748.866    0.04       010250.83    0.04       0
#XS Ineff= 2 , 0
       0                               0
Bank Sta=9748.866,10250.83
Exp/Cntr=0.3,0.1

Type RM Length L Ch R = 1 ,11420.32,265.062200,265.062200,265.062200
XS GIS Cut Line= 6
 905776.39810131791214.463610676905908.069226162 791150.05747599
906073.186406667791108.057976797906120.650326052791091.382661189
906167.252534427  791064.9277033906228.276188032791012.267717945
#Sta/Elev= 30
9745.565 47.40629755.34947.475139766.72447.052059778.09947.176779845.38545.06922
9867.16744.065949899.55141.214979920.50441.073789951.61841.683219961.88442.11044
9972.15141.565919982.418 39.35429989.05838.9768510002.9738.8683510013.2439.65505
10023.5239.6097810044.0743.5335110054.3445.9578410064.6746.9911910075.27 47.6979
10107.0746.9773910127.3147.1819210152.2546.8626310164.0547.1233310176.5246.84511
 10199.247.9943310214.1447.9284410228.7748.6158210242.9143.21035 10247.442.02272
#Mann= 3 , 0 , 0
9745.565    0.04       09745.565    0.04       0 10247.4    0.04       0
#XS Ineff= 2 , 0
       0                               0
Bank Sta=9745.565,10247.4
Exp/Cntr=0.3,0.1

Type RM Length L Ch R = 1 ,11155.26,240.803000,240.803000,240.803000
XS GIS Cut Line= 6
905921.582188122791547.816367368906057.278695129791364.550980584
906074.370849339 791338.42774152906112.847402268791286.665568919
906150.506564809791229.914449282906208.693155816791136.457322812
#Sta/Elev= 30
 9729.2341.647179770.06342.062639785.38742.811329869.60543.015949894.49142.14611
9906.934 41.31239919.82541.09441 9931.8240.14067 9936.6338.716179944.26335.85204
9953.43534.464159957.264 34.63939968.79334.244519971.05134.323329981.21235.90506
9988.49535.799539992.76634.9718210005.23 34.266410023.0739.1095610042.6140.19751
10066.9939.9895310078.9941.0969510090.9943.17337   1010344.0681210138.6745.10861
10148.5244.7836110174.0144.9107810205.2844.4989810221.1345.5610810231.1945.26856
#Mann= 3 , 0 , 0
 9729.23    0.04       0 9729.23    0.04       010231.19    0.04       0
#XS Ineff= 2 , 0
       0                               0
Bank Sta=9729.23,10231.19
Exp/Cntr=0.3,0.1

Type RM Length L Ch R = 1 ,10914.45,237.994100,237.994100,237.994100
XS GIS Cut Line= 6
 906303.98393035 791561.69894682906320.525154714791479.656173172
906320.986003633791409.148886691906269.625186453791248.164375057
906261.801962554791193.462033535906290.706533414791075.143797731
#Sta/Elev= 30
9749.07938.150679766.26438.359529776.55437.82903 9796.9737.825189827.40237.13562
9872.11336.612849917.82735.483319927.99435.955679938.35534.949629948.71632.50903
9959.32331.587489980.60533.301019991.24632.219849996.59132.6779610033.9736.83839
10055.1640.1870410065.6340.7873310076.02 40.805510086.2539.9291810096.4839.38588
10106.5241.5603610116.5642.6441510136.6243.3521510146.6344.2591310197.6944.27132
10208.2143.3449410218.7240.8386110229.3338.8382610240.1939.48902 10250.938.70167
#Mann= 3 , 0 , 0
9749.079    0.04       09749.079    0.04       0 10250.9    0.04       0
#XS Ineff= 2 , 0
       0                               0
Bank Sta=9749.079,10250.9
Exp/Cntr=0.3,0.1

Type RM Length L Ch R = 1 ,10676.46,237.994100,237.994100,237.994100
XS GIS Cut Line= 6
906363.717268189791557.320105459906401.908224978791468.148780357
906436.180512905791411.751720135906467.532805152791377.711520923
906570.611896393791289.761519018906660.334902538791161.601366779
#Sta/Elev= 30
9749.07836.690989773.15436.813239838.57435.961859892.38332.931729954.93432.26433
9967.93932.606749980.57131.978689993.20430.78591   1000128.2866410005.7427.23736
10012.2628.7609410018.32 30.820810028.7433.2814410044.1734.4242310072.6135.17255
10086.8335.2221610100.4737.27651 10113.538.1252510126.4237.8012910151.2837.93265
10163.7138.4724210175.6337.82747 10187.536.7942610199.3836.3443610211.2537.99445
10223.1338.20593   1023537.6609110241.0238.7129610246.8839.2950610250.9138.86455
#Mann= 3 , 0 , 0
9749.078    0.04       09749.078    0.04       010250.91    0.04       0
#XS Ineff= 2 , 0
       0                               0
Bank Sta=9749.078,10250.91
Exp/Cntr=0.3,0.1

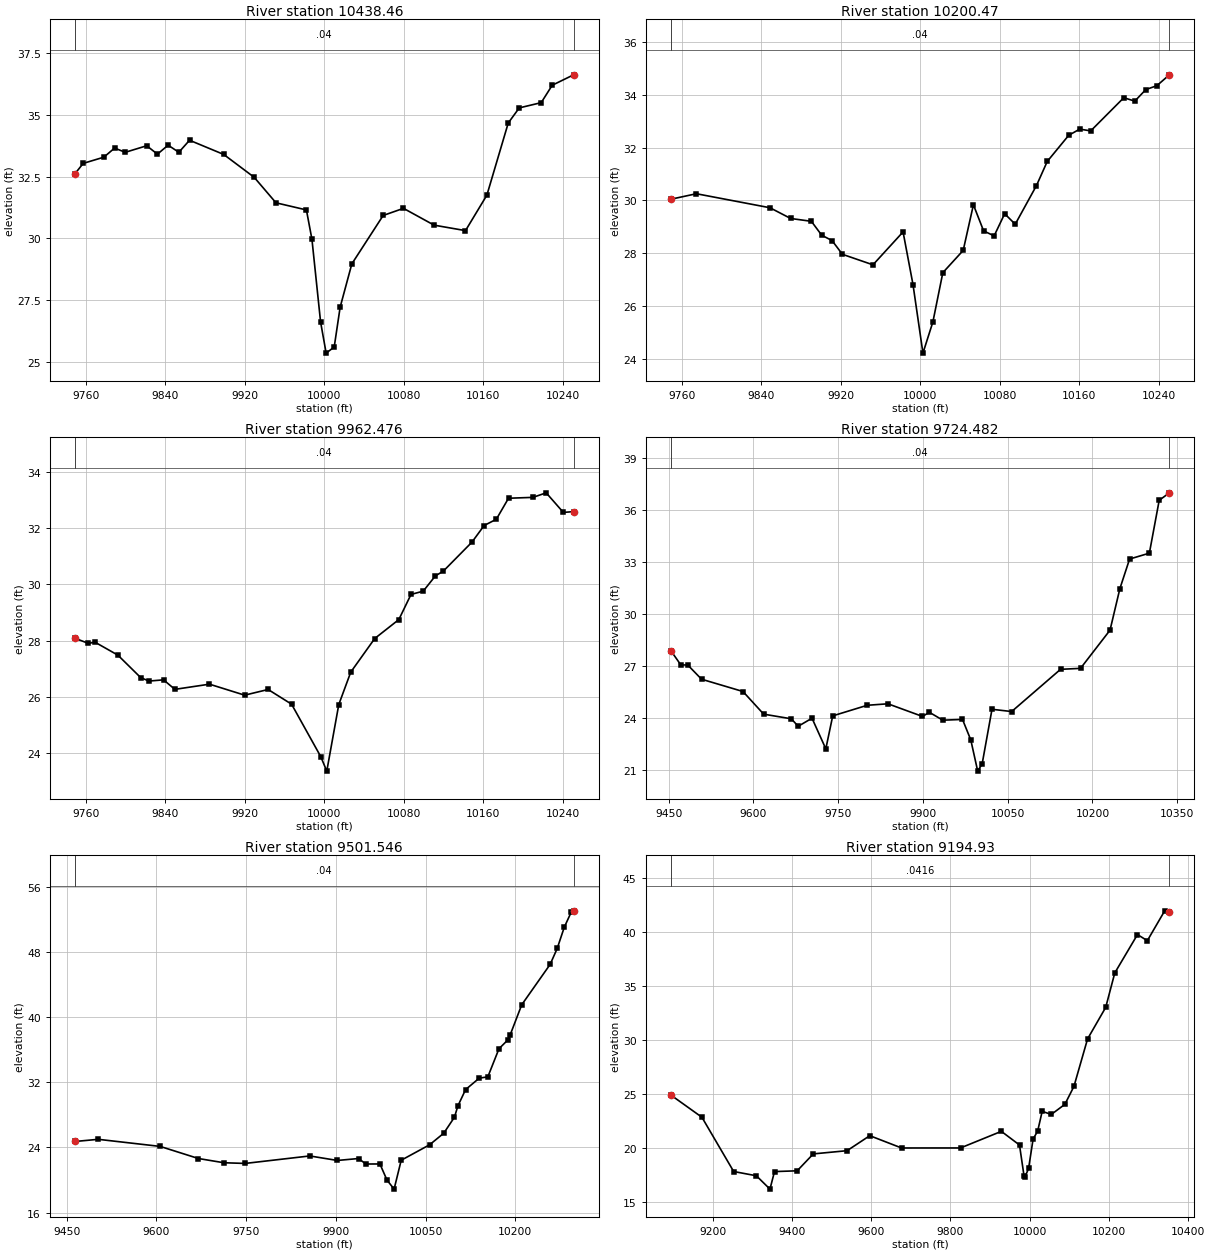
Type RM Length L Ch R = 1 ,10438.46,237.994100,237.994100,237.994100
XS GIS Cut Line= 6
906551.903568474791731.986916606906628.298018532791546.089146119
906643.699300585791520.299598701906677.011555983791481.886312269
906702.252605612791382.945921532906749.272630114791275.555254006
#Sta/Elev= 30
9749.10532.611749757.41533.029469778.18733.279519788.96333.646659799.73933.47604
9821.29133.740129832.06733.401029842.84333.763999853.619 33.47659864.39633.96228
9898.77233.389989929.45632.467359951.37631.439119982.00231.151459987.57429.96536
9996.27326.6302210001.8625.3766910009.9725.6232410015.9527.22974 10027.728.97567
10059.2330.9281410079.6831.21586 10110.530.5376310142.0930.31727 10163.6 31.7471
10185.1134.6582210196.1735.2667510218.2835.4788110229.3436.1800110250.8536.60049
#Mann= 3 , 0 , 0
9749.105    0.04       09749.105    0.04       010250.85    0.04       0
#XS Ineff= 2 , 0
       0                               0
Bank Sta=9749.105,10250.85
Exp/Cntr=0.3,0.1

Type RM Length L Ch R = 1 ,10200.47,237.994200,237.994200,237.994200
XS GIS Cut Line= 6
906797.422538018791769.390327245906853.749491164791593.541590349
906861.201135218791504.065610525 906870.34564931 791464.79051641
906901.750018471791382.942439022 906944.56992345  791293.6579987
#Sta/Elev= 30
9749.087 30.04379774.89830.25246 9848.9329.722589869.76529.316919890.60129.20979
9901.01928.684149911.43728.479789921.85527.961739952.59827.564019982.89628.80874
9992.896 26.8167 10002.924.22424 10012.925.4032810022.9127.2669910043.4228.10895
10053.6929.8352110063.9528.8466110074.5528.6585810085.1629.4968410095.7729.09831
10117.1830.56329   1012831.4736810149.6432.4632110160.6732.6959110171.7632.62938
10205.0433.8835810216.1333.7554710227.2234.1918710238.3134.3380110250.8934.74949
#Mann= 3 , 0 , 0
9749.087    0.04       09749.087    0.04       010250.89    0.04       0
#XS Ineff= 2 , 0
       0                               0
Bank Sta=9749.087,10250.89
Exp/Cntr=0.3,0.1

Type RM Length L Ch R = 1 ,9962.476,237.994100,237.994100,237.994100
XS GIS Cut Line= 6
906928.377905671791862.627723338906988.728680551791755.679882327
907056.354802966791647.966887906907057.408121357791646.266734864
907093.932652139791592.179393734907200.973787734791441.621268571
#Sta/Elev= 30
9749.01728.081699762.49127.900149769.25727.940349792.22227.480449815.18726.67998
9823.53526.556769838.15126.600139849.63426.261529884.42826.44591 9919.8526.05436
9943.46526.256569967.08125.733169996.45223.8651410002.5323.34779 10014.625.71862
10026.6626.8746210050.7928.0720810075.0728.7474310087.3429.6438310099.6129.75952
10111.8830.3042110119.8830.4738810148.6931.5071810160.9632.0985910173.2332.32203
 10185.5 33.070810210.04 33.101610223.43 33.263710240.6932.56603   1025132.59404
#Mann= 3 , 0 , 0
9749.017    0.04       09749.017    0.04       0   10251    0.04       0
#XS Ineff= 2 , 0
       09750.083                       0
Bank Sta=9749.017,10251
Exp/Cntr=0.3,0.1

Type RM Length L Ch R = 1 ,9724.482,222.936200,222.936200,222.936200
XS GIS Cut Line= 2
 906938.37557608792229.618067752907445.320020524 791507.39584553
#Sta/Elev= 30
 9453.8227.90483 9471.6827.074659483.89727.071959508.33226.252179581.63825.54313
9618.29124.237259667.16123.970489679.379 23.53979703.814 24.00489728.24922.23771
9740.46724.139329801.55524.749749838.20724.834919899.29524.107299911.51324.34487
9935.30923.890249970.12123.934799984.818 22.75199997.03620.9543210004.9321.37502
10022.3424.5188210057.1524.3885610143.6526.8225910178.99 26.877510231.2129.07987
10248.62 31.470110265.8233.1784910300.8333.5175310318.24 36.5643 10336.2 36.9951
#Mann= 3 , 0 , 0
 9453.82    0.04       0 9453.82    0.04       0 10336.2    0.04       0
#XS Ineff= 2 , 0
       09802.895                       0
Bank Sta=9453.82,10336.2
Exp/Cntr=0.3,0.1

Type RM Length L Ch R = 1 ,9501.546,306.615400,306.615400,306.615400
XS GIS Cut Line= 2
907144.104742746792365.034734419907592.021409413791661.909734419
#Sta/Elev= 30
 9463.7324.726739502.62124.992289606.051 24.12369670.13122.637239712.76222.11719
9748.33222.034029856.254  22.9529902.469 22.39859938.03922.637579949.89621.96196
 9973.6121.968569985.46619.986099997.32318.8809410009.1822.4262510056.6124.31846
10080.3225.7399310098.2127.7066510104.0329.1015110116.8331.09288 10139.632.49544
10154.0532.6600710172.66 36.106910187.0337.1551710191.2737.7863310210.7441.50577
10258.1746.4539910270.0348.4136110281.8851.0224910293.7452.91276 10297.4   53.03
#Mann= 3 , 0 , 0
 9463.73    0.04       0 9463.73    0.04       0 10297.4    0.04       0
#XS Ineff= 2 , 0
       09566.058                       0
Bank Sta=9463.73,10297.4
Exp/Cntr=0.3,0.1

Type RM Length L Ch R = 1 , 9194.93,431.498500,431.498500,431.498500
XS GIS Cut Line= 2
907230.042242746792893.680567752907842.021409413791794.722234419
#Sta/Elev= 30
9094.52924.950939173.14122.890249253.26217.867239310.492 17.4734 9344.8316.23663
9356.276 17.85999413.50617.932659454.13819.497189539.41219.795129596.64221.18312
9676.76420.045519825.56220.047799928.57621.58514 9974.3620.320769985.80617.45411
9988.54417.394249997.25218.14824 10008.720.8797210020.1421.6001410031.5923.43824
10054.4823.1486910088.8224.0834110111.7125.7459210146.05 30.137210191.8333.05775
10214.7336.2465310271.9639.7975210296.8639.2328410340.6341.99543 10352.4 41.8647
#Mann= 3 , 0 , 0
9094.529  0.0416       09094.529  0.0416       0 10352.4  0.0416       0
#XS Ineff= 2 , 0
       09620.884                       0
Bank Sta=9094.529,10352.4
Exp/Cntr=0.3,0.1

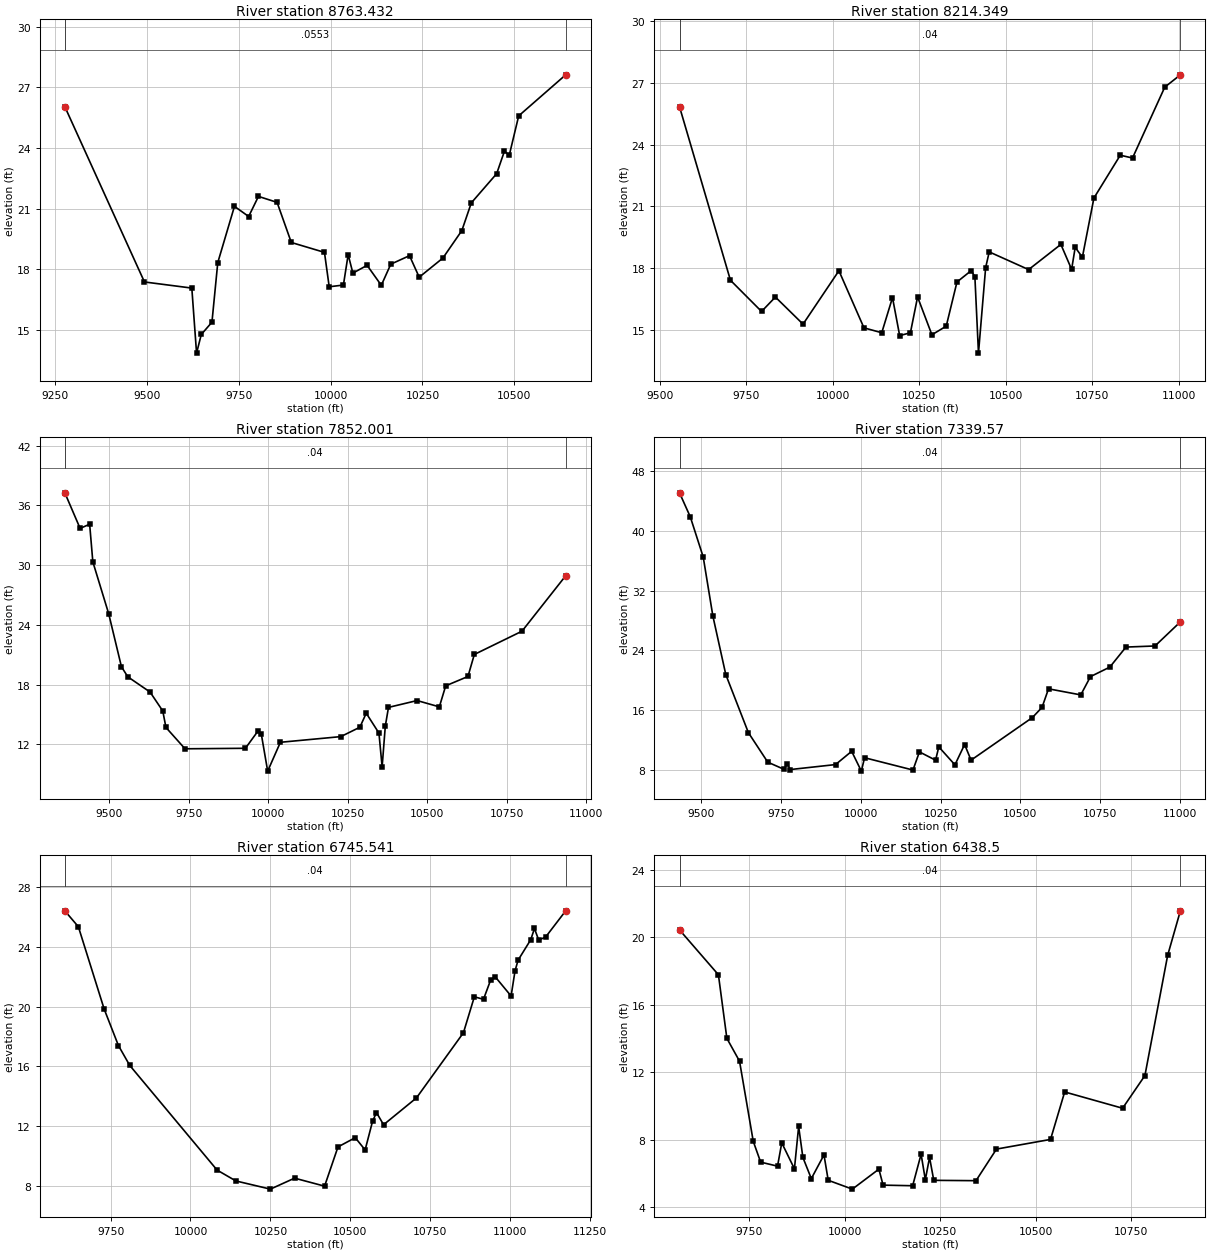
Type RM Length L Ch R = 1 ,8763.432,549.082700,549.082700,549.082700
XS GIS Cut Line= 2
 907461.81307608793003.055567752908323.792242746791945.763901086
#Sta/Elev= 30
9275.94626.036729492.77517.369739621.79717.066929634.699 13.85089647.60114.77408
9676.63115.381059692.45718.324529737.916 21.10919776.62320.606519803.23621.60119
9854.03621.305739892.74319.322519983.05818.83306 9995.9617.1318410034.6717.21757
10047.5718.7211610060.4717.8072910099.1818.1918210137.88 17.204610163.6918.24925
 10214.718.66965 10241.117.6055610305.6118.5522310357.2219.9104210383.0321.28116
10452.09 22.725210473.3423.8437810486.2423.6281910512.0525.5828110640.0827.61249
#Mann= 3 , 0 , 0
9275.946  0.0553       09275.946  0.0553       010640.08  0.0553       0
#XS Ineff= 2 , 0
       09756.697           10156       0
Bank Sta=9275.946,10640.08
Exp/Cntr=0.3,0.1

Type RM Length L Ch R = 1 ,8214.349,362.347700,362.347700,362.347700
XS GIS Cut Line= 5
908195.757229984793352.334247917908199.663480014792963.011331245
908165.809313297792862.750914574908155.392646641 792806.76133126
908390.599946916791941.427828431
#Sta/Elev= 30
9556.34225.839739703.68417.414489793.68815.89875 9833.6916.598989913.69515.28259
10017.4717.8768810089.9115.1043710141.3714.8665110172.4616.5732110193.1814.72777
10224.27 14.8648   1024516.6046610286.4514.76716 10327.9 15.186810358.99 17.3303
10400.4417.88697 10410.817.5740910421.1713.8766610441.8918.0266210452.2618.79097
10566.25 17.931810659.5119.15566 10690.617.9424810700.96 19.011210721.6918.53238
10755.0921.4057910831.3423.4849910866.7723.3492310960.0326.7888811005.1927.38792
#Mann= 3 , 0 , 0
9556.342    0.04       09556.342    0.04       011005.19    0.04       0
#XS Ineff= 2 , 0
       09987.952        10131.16       0
Bank Sta=9556.342,11005.19
Exp/Cntr=0.3,0.1

Type RM Length L Ch R = 1 ,7852.001,512.431000,512.431000,512.431000
XS GIS Cut Line= 2
 908547.75057608793503.055567752908529.521409413791927.534734419
#Sta/Elev= 30
9359.87837.265989407.93733.692279437.93934.110649447.93930.337249497.94325.10516
9537.94519.790969557.94718.778079627.95117.246749667.95415.346759677.95513.68958
9737.959 11.54389927.97211.594699967.97413.351559977.97513.014699997.9769.299512
10037.9812.1982210227.9912.76742   1028813.71011   1030815.12069   1034813.12149
   103589.728702   10368 13.8177   1037815.7047110468.0116.3915310538.0115.75862
10558.0117.8719710628.02 18.810810648.0221.0231410798.0323.36271 10935.528.93266
#Mann= 3 , 0 , 0
9359.878    0.04       09359.878    0.04       0 10935.5    0.04       0
#XS Ineff= 2 , 0
       0                10260.67       0
Bank Sta=9359.878,10935.5
Exp/Cntr=0.3,0.1

Type RM Length L Ch R = 1 , 7339.57,594.029500,594.029500,594.029500
XS GIS Cut Line= 2
909138.896409413793388.472234419908896.708909413791836.388901086
#Sta/Elev= 30
9431.03345.067279464.91141.847879505.39536.483759535.758 28.57679576.24220.75943
9647.08912.999349707.8159.057495 9758.428.1071519768.5418.8359129778.6628.070458
9920.3568.7336259970.96110.5075110001.327.85824110011.45 9.6498710163.268.004512
 10183.510.4289510234.119.32299510244.2311.0998410294.838.699846 10325.211.41744
10345.449.32648610537.7415.01929 10568.116.3873410588.3418.8631810689.55 18.0497
10719.9220.4958710780.6421.7655110831.25  24.44510922.3424.59139 11001.927.81417
#Mann= 3 , 0 , 0
9431.033    0.04       09431.033    0.04       0 11001.9    0.04       0
#XS Ineff= 2 , 0
       0                10218.52       0
Bank Sta=9431.033,11001.9
Exp/Cntr=0.3,0.1

Type RM Length L Ch R = 1 ,6745.541,307.041000,307.041000,307.041000
XS GIS Cut Line= 6
909831.969701869793077.047187344909814.861333484792940.180240264
909772.090412521792871.746766724909489.802334168792632.229609333
909310.164466125792191.689123419909019.322203579791785.365374274
#Sta/Elev= 30
9606.90626.39822 9649.2825.335669729.90319.836319774.53117.395769809.90916.06828
 10083.29.07158310142.048.34394110250.027.79724710325.718.53091710419.527.995656
10461.4610.6188510515.5211.2366510546.3710.4168110569.6812.3386810581.9412.91581
10604.0912.1005810707.0913.8976310853.9118.2497310888.0920.6530110916.7220.48602
10939.3621.7923610953.71 21.980511003.0420.7059811015.3722.3853611024.8223.09848
11064.6924.4765111076.0925.2197811089.3524.4474111110.9124.6438511173.8826.39973
#Mann= 3 , 0 , 0
9606.906    0.04       09606.906    0.04       011173.88    0.04       0
#XS Ineff= 2 , 0
       0                10136.38       0
Bank Sta=9606.906,11173.88
Exp/Cntr=0.3,0.1

Type RM Length L Ch R = 1 ,  6438.5,745.203800,745.203800,745.203800
XS GIS Cut Line= 2
910086.863635338792997.146908614909530.862938361791811.012088396
#Sta/Elev= 30
9568.02320.433929669.79217.77274 9691.88 14.00289725.01212.649749760.9017.897296
9780.2336.6646399824.4096.4251439835.4537.8080979868.5866.267767 9879.638.779228
9890.6746.9451519912.7625.6868539945.8957.0930289956.9395.58855310020.075.063846
10089.476.24808910100.515.30034110177.825.26463210199.917.13478710210.955.621056
   102226.94387210233.045.58505110343.485.56458910397.047.43781110538.418.010233
10575.4110.8250310726.899.85921210785.2511.79547 10844.718.9192210878.0121.56369
#Mann= 3 , 0 , 0
9568.023    0.04       09568.023    0.04       010878.01    0.04       0
#XS Ineff= 2 , 0
       0                10320.84       0
Bank Sta=9568.023,10878.01
Exp/Cntr=0.3,0.1

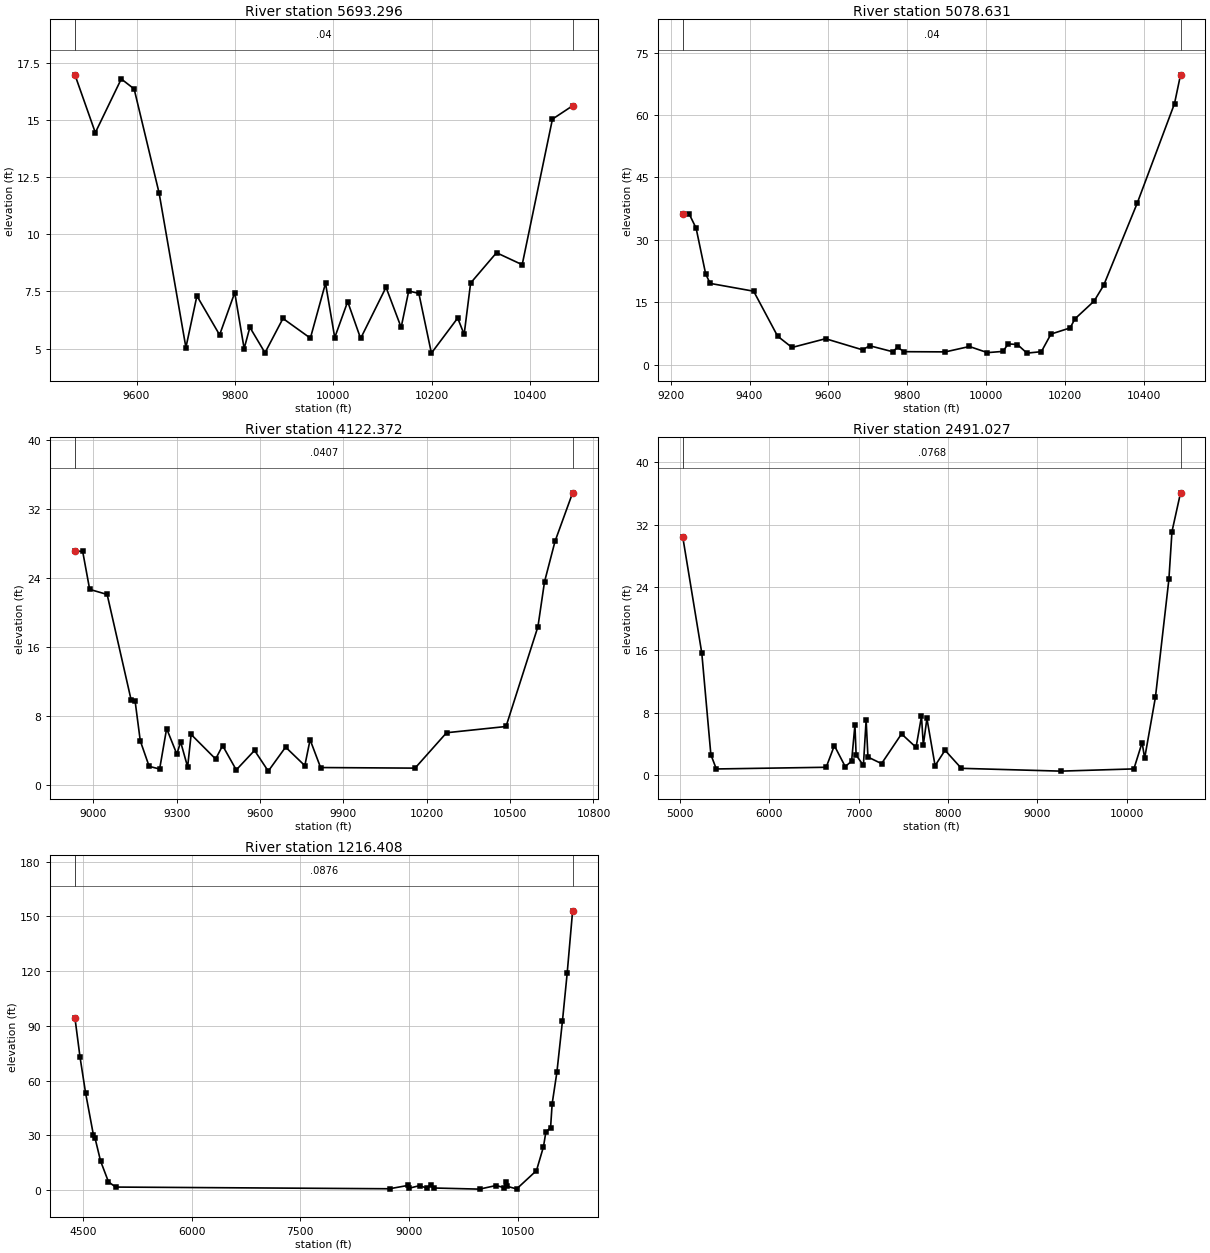
Type RM Length L Ch R = 1 ,5693.296,614.665300,614.665300,614.665300
XS GIS Cut Line= 2
910726.264436861792436.512872495910068.330278772791667.378575011
#Sta/Elev= 30
9474.67616.966139516.14614.438469568.92416.786469595.10416.348859645.84311.80383
 9700.385.0524599722.7617.3069789768.9135.603099 9799.687.4496379818.8165.004203
9830.4485.9350529861.2154.8223529897.7746.3206179953.517 5.461089984.2857.861842
10003.055.48686210029.377.05719910055.695.44758210107.357.68426810138.125.930835
10153.517.52247310174.137.41595610199.664.80697710253.086.33901510266.245.626242
 10279.47.86914210332.049.19338710384.268.670741 10445.815.0312710486.8315.61365
#Mann= 3 , 0 , 0
9474.676    0.04       09474.676    0.04       010486.83    0.04       0
#XS Ineff= 2 , 0
       0                               0
Bank Sta=9474.676,10486.83
Exp/Cntr=0.3,0.1

Type RM Length L Ch R = 1 ,5078.631,956.259000,956.259000,956.259000
XS GIS Cut Line= 2
911254.465098989 792232.64595027910536.297532061 791194.77798258
#Sta/Elev= 30
9230.86736.196629247.50136.117569264.48632.834639288.80821.805329300.22319.55869
9410.41417.686849471.2176.8892879507.6994.1759569592.8246.2803369686.8543.601933
9704.4284.5971029763.0733.1544329775.2344.2055619792.2983.164215 9896.843.116235
9957.6434.41187510003.192.93727510042.773.23455910055.915.03650610079.254.884445
10103.572.81779210140.053.16769410164.37 7.3905610213.028.87138810225.1811.04453
10273.8215.3130310298.14 19.115210383.2738.8520610477.6962.7302110492.9869.64275
#Mann= 3 , 0 , 0
9230.867    0.04       09230.867    0.04       010492.98    0.04       0
#XS Ineff= 2 , 0
       0                               0
Bank Sta=9230.867,10492.98
Exp/Cntr=0.3,0.1

Type RM Length L Ch R = 1 ,4122.372,1631.345000,1631.345000,1631.345000
XS GIS Cut Line= 2
912157.966231576791797.112070972 911069.13153333 790374.67695454
#Sta/Elev= 30
8933.67327.13718 8961.5227.115658986.70722.695519049.67422.101929135.9759.840141
9150.4219.6718569168.8795.0935649200.7952.1309819238.5751.8161549263.7626.518371
9300.494 3.549239314.1364.9706259339.323 2.056759351.9165.835531 9440.072.982096
9465.2574.5368139514.3681.7137599580.175 3.980859629.5311.5732569691.9394.363035
9761.1462.2107949780.0935.2243359817.8741.989532 10157.91.92180110271.246.034376
10485.336.75936510600.1918.3633510623.8523.5720610661.63 28.270110725.0133.91347
#Mann= 3 , 0 , 0
8933.673  0.0407       08933.673  0.0407       010725.01  0.0407       0
#XS Ineff= 2 , 0
       0                               0
Bank Sta=8933.673,10725.01
Exp/Cntr=0.3,0.1

Type RM Length L Ch R = 1 ,2491.027,1274.618700,1274.618700,1274.618700
XS GIS Cut Line= 4
917693.791141421791686.388017838915161.301658248 791230.26760017
914262.676357767791080.496716756 912451.81022195790045.716067718
#Sta/Elev= 30
5032.82530.395085244.97615.608855346.5852.617768 5407.550.7926026637.0191.009105
6728.467 3.781986850.3981.0911876921.5241.7927586958.7916.4165296972.3282.551529
7053.6161.2563937084.0987.053685 7104.422.3149297256.8341.4767377480.3735.276085
7642.8643.5529757703.6927.5177647723.9683.865787 7764.527.2455837855.7611.213166
7967.2783.1830018149.7610.8735459263.0450.51556810080.790.80030510172.934.174828
10201.082.16038410322.019.98023810472.38 25.024910506.9431.1424210602.7536.10293
#Mann= 3 , 0 , 0
5032.825  0.0768       05032.825  0.0768       010602.75  0.0768       0
#XS Ineff= 2 , 0
       0  9248.7                       0
Bank Sta=5032.825,10602.75
Exp/Cntr=0.3,0.1

Type RM Length L Ch R = 1 ,1216.408,0.000000,0.000000,0.000000
XS GIS Cut Line= 2
  918469.8766282791427.692855578912165.883989978 788718.20141928
#Sta/Elev= 30
4392.70394.402734463.31872.76471 4539.5153.217044648.35629.964914670.12528.37121
4746.31715.826924855.1624.4239744953.1231.546974 8730.060.6176338980.4042.415763
9002.1730.9329839143.6722.3230189252.5180.8509599296.0562.9504079339.5941.031646
9970.8970.414991 10198.8 2.3911810308.321.24636310330.094.12930110351.861.967434
10482.470.52073110755.9310.5805910852.5523.67343 10885.231.6928910950.5134.18168
10972.2847.2920411037.5864.5615311113.7792.4926211179.08118.791211254.31153.0968
#Mann= 3 , 0 , 0
4392.703  0.0876       04392.703  0.0876       011254.31  0.0876       0
#XS Ineff= 2 , 0
       08428.073                       0
Bank Sta=4392.703,11254.31
Exp/Cntr=0.3,0.1